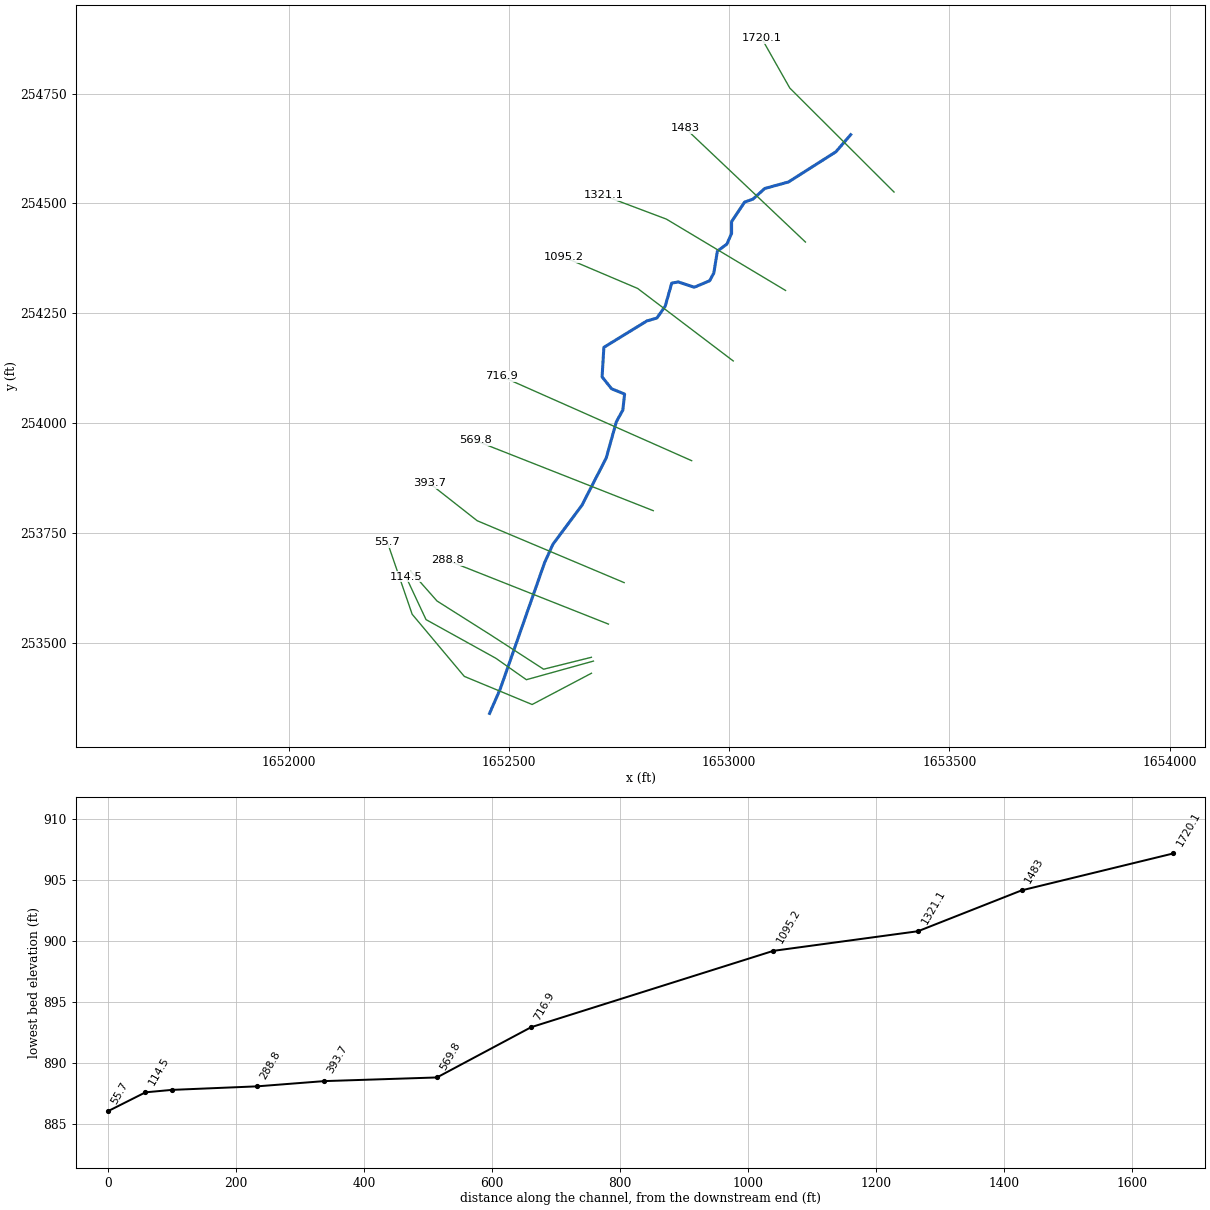
--- JOHNSONFK.prj (project) ---

Proj Title=JOHNSONFK
Current Plan=p01
Default Exp/Contr=0,0
English Units
Geom File=g01
Flow File=f01
Plan File=p01
BEGIN DESCRIPTION:
END DESCRIPTION:
DSS Export Rating Curves= 0
DSS Export Rating Curve Sorted= 0
DSS Export Volume Flow Curves= 0
DXF OffsetX= 0
DXF OffsetY= 0
DXF ScaleX= 0
DXF ScaleY= 0

--- JOHNSONFK.p01 (plan) ---

Plan Title=Floodplain
Program Version=4.00
Geom File=g01
Flow File=f01
K Sum by GR=0
Std Step Tol=0.01
Critical Tol=0.01
Num of Std Step Trials=20
Max Error Tol=0.3
Flow Tol Ratio=0.001
Split Flow NTrial=30
Split Flow Tol=0.02
Split Flow Ratio=0.02
Log Output Level=0
Friction Slope Method=1
Unsteady Friction Slope Method=2
Unsteady Bridges Friction Slope Method=1
Global Log Level=0
CheckData=False
Run HTab=0
Run UNet=0
Run PostProcess=0
UNET Theta=0
UNET Theta Warmup=0
UNET ZTol=0
UNET ZSATol=0
UNET MxIter=0
UNET MaxInSteps=0
UNET DtIC=0
UNET DtMin=0
UNET MaxCRTS=0
UNET WFStab=0
UNET SFStab=0
UNET WFX=0
UNET SFX=0
UNET DSS MLevel=0
UNET DZMax Abort=0
UNET Convert EG Bridges=0
UNET Use Existing IB Tables=0
UNET Froude Limit=0
UNET Froude Power=0
Write IC File=0
Echo Input=False
Echo Output=False
Write Detailed=0

--- JOHNSONFK.f01 (steady flow) ---

Flow Title=NFF Regression Equation
Program Version=4.10
Number of Profiles= 1
Profile Names=P100yr
River Rch & RM=JOHNSONFK,Main            ,1720.1
645.0575
River Rch & RM=JOHNSONFK,Main            ,569.8
714.1412
River Rch & RM=JOHNSONFK,Main            ,288.8
716.7994
Boundary for River Rch & Prof#=JOHNSONFK,Main            , 1
Up Type= 0
Dn Type= 3
Dn Slope=0.02666
DSS Import GetInterval= 0
DSS Import GetPeak= 0
DSS Import FillOption= 0

--- JOHNSONFK.g01 (geometry) ---

Geom Title=USGS 10m DEM
Program Version=4.10

River Reach=JOHNSONFK       ,Main
Reach XY= 30
     1653276.171       254656.51     1653242.533      254617.491
     1653134.893       254548.87     1653081.072      254534.069
     1653054.162       254509.85     1653035.325      254503.123
     1653005.724      254458.721     1653005.724      254431.811
      1652994.96      254407.592     1652973.432      254391.446
     1652965.359      254341.662      1652955.94       254324.17
     1652920.957       254309.37     1652884.628      254321.479
     1652869.828      254318.788     1652855.027      254266.314
      1652836.19      254239.403     1652813.317      254232.676
     1652715.767      254172.666     1652711.731      254105.391
     1652733.259      254078.481      1652762.86      254066.371
     1652758.824      254030.042     1652744.023      254003.132
     1652721.149      253921.056     1652665.984      253813.416
     1652600.054      253724.612     1652581.217      253682.902
     1652480.304      253394.963     1652456.314      253339.979

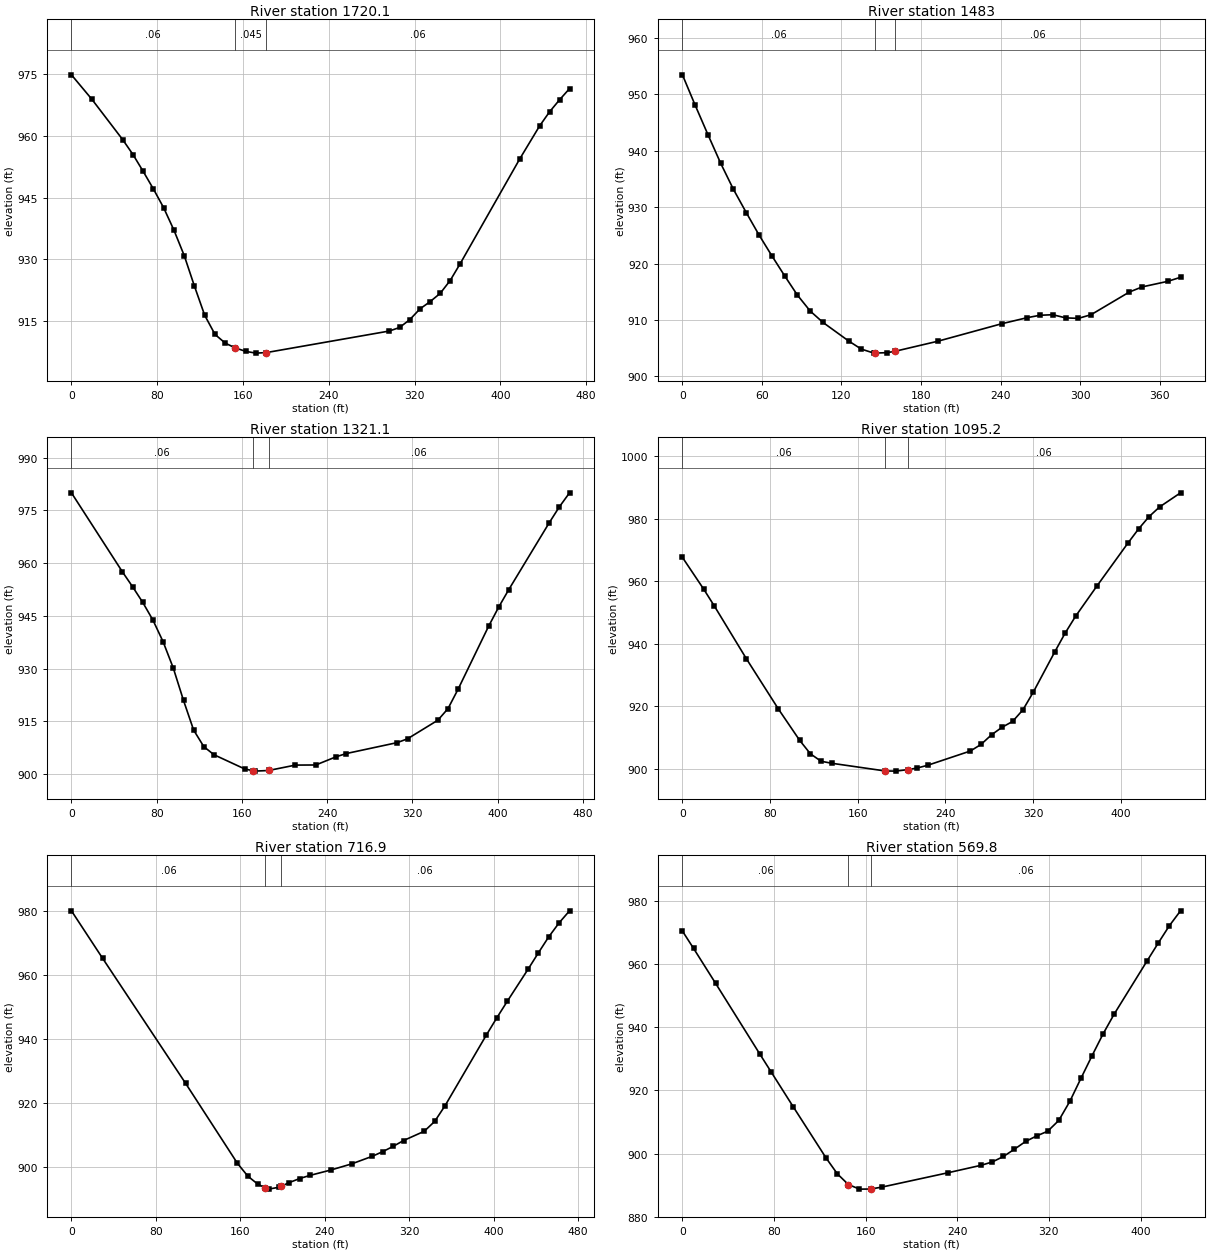
Type RM Length L Ch R = 1 ,1720.1  ,236.3,237.1,237.7
XS GIS Cut Line= 3
     1653374.464      254525.947     1653137.829      254762.583
     1653073.989      254875.634
#Sta/Elev= 30
       0  974.92    19.1  968.95    47.8  959.14    57.4  955.51    66.9  951.41
    76.5   947.1      86  942.56    95.6   937.1   105.2   930.9   114.7  923.48
   124.3  916.36   133.9  911.72   143.4  909.61   152.6  908.46   162.6  907.59
   172.1  907.17   181.7   907.3   296.4  912.55     306  913.41   315.5  915.32
   325.1  917.95   334.6  919.73   343.9  921.72   353.2  924.85   362.5  928.93
   418.1  954.46   436.7  962.52   445.9  965.92   455.2  968.84   464.5  971.56
#Mann= 3 , 0 , 0
       0     .06       0   152.6    .045       0   181.7     .06       0
Bank Sta=152.6,181.7
XS Rating Curve= 0 ,0
Exp/Cntr=0.3,0.1

Type RM Length L Ch R = 1 ,1483    ,156,161.9,167.5
XS GIS Cut Line= 2
     1653173.374      254412.235     1652900.805      254670.915
#Sta/Elev= 30
       0  953.47     9.6  948.09    19.3  942.84    28.9  937.77    38.5  933.16
    48.2  929.03    57.8  925.08    67.4  921.42    77.1  917.85    86.7  914.44
    96.4   911.6     106  909.59   125.3  906.31   134.9  904.86   144.5  904.14
   145.3  904.15   154.2  904.22   160.3  904.46   192.7  906.25   240.9  909.35
   260.2  910.43   269.8  910.85   279.4  910.95   289.1  910.39   298.7   910.3
   308.3  910.95   337.2  914.97   346.9  915.88   366.1  916.86   375.8  917.58
#Mann= 3 , 0 , 0
       0     .06       0   145.3    .045       0   160.3     .06       0
Bank Sta=145.3,160.3
XS Rating Curve= 0 ,0
Exp/Cntr=0.3,0.1

Type RM Length L Ch R = 1 ,1321.1  ,228.5,226,224.5
XS GIS Cut Line= 3
     1653128.219      254302.094     1652857.668      254464.379
     1652715.326      254518.139
#Sta/Elev= 30
       0  980.01    47.8  957.54    57.4  953.28    66.9  948.84    76.5  943.78
      86  937.66    95.6  930.14   105.2  920.92   114.7  912.48   124.3  907.75
   133.8  905.46   162.5  901.43     170  900.93   172.1  900.79     185  900.97
   210.3  902.51   229.4  902.54   248.6  904.89   258.1   905.8   305.9  908.91
   315.5  909.99     344  915.29   353.5  918.58     363  924.12   391.6  942.01
   401.1  947.48   410.6  952.48   448.6  971.52   458.1  976.04   467.6  980.01
#Mann= 3 , 0 , 0
       0     .06       0     170    .045       0     185     .06       0
Bank Sta=170,185
XS Rating Curve= 0 ,0
Exp/Cntr=0.3,0.1

Type RM Length L Ch R = 1 ,1095.2  ,373.1,378.3,380.5
XS GIS Cut Line= 3
      1653009.41      254141.711     1652792.484      254306.647
     1652624.865      254377.929
#Sta/Elev= 30
       0  967.62    19.5  957.41    29.2  952.01    58.4  935.15    87.6  919.06
   107.1  908.99   116.8  904.73   126.5  902.35   136.2   901.7   184.9  899.24
   194.6  899.18   205.6  899.65   214.1  900.16   223.8  901.05   262.8  905.62
   272.5  907.72   282.1  910.81   291.7  913.22   301.3  915.08   310.8  918.82
   320.4  924.59   339.6  937.22   349.2  943.32   358.8  948.76     378  958.31
   406.7  972.25   416.3  976.73   425.9  980.69   435.5  983.78   454.6   988.3
#Mann= 3 , 0 , 0
       0     .06       0   184.9    .045       0   205.6     .06       0
Bank Sta=184.9,205.6
XS Rating Curve= 0 ,0
Exp/Cntr=0.3,0.1

Type RM Length L Ch R = 1 ,716.9   ,146.2,147.1,148
XS GIS Cut Line= 2
     1652915.111      253914.816     1652483.733      254106.401
#Sta/Elev= 30
       0     980    29.5  965.16   108.2  926.01   157.3  900.99   167.2  896.96
     177  894.37   183.6  893.39   186.8  892.92   196.7  893.51   198.6   893.8
   206.5  894.98   216.3  896.24   226.2  897.23   245.8   898.9   265.5  900.81
   285.2  903.21     295  904.65   304.8  906.29   314.7  908.12   334.3  911.02
   344.2   914.1     354     919   393.3   941.2   403.2  946.57     413  951.69
   432.7  961.72   442.5  966.86   452.3  971.86   462.2  976.27     472     980
#Mann= 3 , 0 , 0
       0     .06       0   183.6    .045       0   198.6     .06       0
Bank Sta=183.6,198.6
XS Rating Curve= 0 ,0
Exp/Cntr=0.3,0.1

Type RM Length L Ch R = 1 ,569.8   ,176.6,176.1,175.6
XS GIS Cut Line= 2
     1652827.888      253801.123     1652423.374      253960.846
#Sta/Elev= 30
       0  970.42     9.7  964.96      29  953.87    67.6  931.51    77.3  925.96
    96.6  914.93   125.6  898.56   135.3  893.62   144.9  890.25   154.6   888.8
   164.3  888.83     174  889.43     232  893.99   260.9  896.35   270.6   897.4
   280.3  899.13   289.9  901.43   299.6  903.87   309.3  905.63   318.9  907.11
   328.6  910.52   338.3  916.59   347.9   923.8   357.6  930.96   367.2  937.84
   376.9  944.12   405.9   961.1   415.6  966.72   425.2  972.14   434.9  976.83
#Mann= 3 , 0 , 0
       0     .06       0   144.9    .045       0   164.3     .06       0
Bank Sta=144.9,164.3
XS Rating Curve= 0 ,0
Exp/Cntr=0.3,0.1

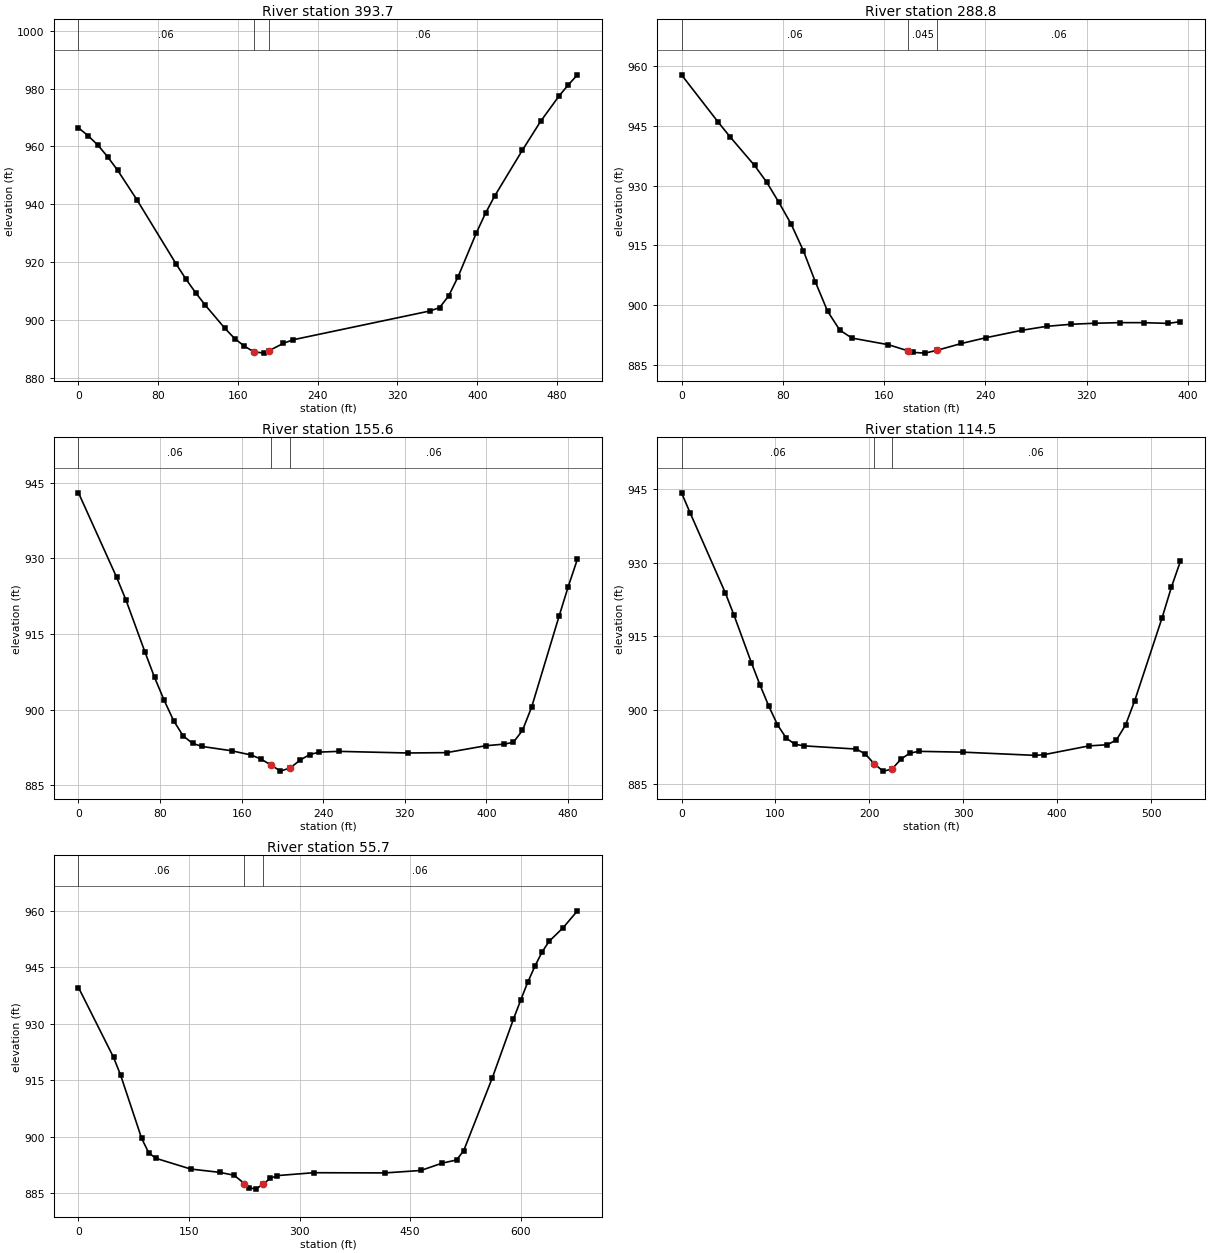
Type RM Length L Ch R = 1 ,393.7   ,104.3,104.9,105.3
XS GIS Cut Line= 3
     1652761.799      253637.452     1652428.086      253778.311
      1652319.44      253863.827
#Sta/Elev= 30
       0  966.45     9.8  963.66    19.6  960.43    29.4  956.35    39.2   951.8
    58.7  941.51    97.9  919.36   107.7  914.15   117.5   909.4   127.3  905.05
   146.8   897.1   156.6  893.56   166.4  890.91   175.8  888.97     186   888.5
   190.8  889.27   205.6   891.9   215.4  893.13   352.4  903.08   362.2  904.24
   371.4  908.34   380.7  914.89   399.1  930.09   408.3  936.93   417.5  942.87
   445.2  958.67   463.6  968.72     482  977.44   491.3  981.31   500.5  984.79
#Mann= 3 , 0 , 0
       0     .06       0   175.8    .045       0   190.8     .06       0
Bank Sta=175.8,190.8
XS Rating Curve= 0 ,0
Exp/Cntr=0.3,0.1

Type RM Length L Ch R = 1 ,288.8   ,137.9,133.2,128.8
XS GIS Cut Line= 2
     1652726.167      253543.061      1652359.75      253688.449
#Sta/Elev= 27
       0   957.7    28.8  945.93    38.5  942.13    57.7  935.02    67.3  930.84
    76.9   925.8    86.5  920.42    96.2  913.74   105.8  905.85   115.4  898.55
     125  893.84   134.6  891.84   163.4  890.18   178.8  888.66   182.7  888.26
   192.3  888.07   201.9  888.78   221.1  890.48   240.4  891.92   269.2   893.8
   288.4  894.77   307.7  895.29   326.9  895.55   346.1   895.7   365.4  895.69
   384.6  895.51   394.2  895.95
#Mann= 3 , 0 , 0
       0     .06       0   178.8    .045       0   201.9     .06       0
Bank Sta=178.8,201.9
XS Rating Curve= 0 ,0
Exp/Cntr=0.3,0.1

Type RM Length L Ch R = 1 ,155.6   ,41.6,41.1,39.7
XS GIS Cut Line= 5
      1652687.48      253467.573     1652578.973      253440.446
      1652458.53      253518.571     1652337.003      253595.611
     1652277.541      253663.103
#Sta/Elev= 30
       0  943.01    37.3  926.29    46.6  921.71    65.2   911.4    74.6  906.37
    83.9  901.88    93.2  897.82   102.5   894.8   111.8  893.29   121.4  892.67
   150.1  891.82   169.3  890.98   178.8  890.18   188.6  889.01     198  887.78
   207.6  888.41   217.1  889.94   226.7  891.07   236.3  891.56   255.4   891.7
   322.6  891.38   360.9  891.45   399.3  892.82   417.3  893.14   426.3  893.49
   435.3  895.85   444.3  900.49   471.3   918.6   480.2  924.41   489.2  929.86
#Mann= 3 , 0 , 0
       0     .06       0   188.6    .045       0   207.6     .06       0
Bank Sta=188.6,207.6
XS Rating Curve= 0 ,0
Exp/Cntr=0.3,0.1

Type RM Length L Ch R = 1 ,114.5   ,53.8,58.7,64.1
XS GIS Cut Line= 5
     1652692.124      253458.936     1652539.911      253416.575
     1652470.466      253465.403     1652312.046      253553.294
     1652266.625      253650.472
#Sta/Elev= 30
       0  944.26     9.3  940.12    46.5  923.95    55.8  919.39    74.4  909.66
    83.6  905.11    92.9  900.83   102.2  897.02   111.5   894.3   120.8  893.06
   130.1  892.73   186.3  892.07   195.7  891.06   205.2  889.07   214.6  887.58
     224  887.96   233.5  889.99   242.9  891.22   252.4  891.61   300.1  891.44
   376.4  890.79   385.9  890.93   433.8  892.72   453.3  892.95   463.1  893.93
   472.8  896.96   482.6  901.94   511.8  918.85   521.6  925.02   531.3  930.36
#Mann= 3 , 0 , 0
       0     .06       0   205.2    .045       0     224     .06       0
Bank Sta=205.2,224
XS Rating Curve= 0 ,0
Exp/Cntr=0.3,0.1

Type RM Length L Ch R = 1 ,55.7    ,56.1,55.7,55.3
XS GIS Cut Line= 5
     1652687.632      253431.288     1652552.932      253360.151
     1652398.852       253424.17     1652280.574      253565.485
     1652224.154      253729.799
#Sta/Elev= 30
       0  939.61    47.6  921.05    57.1  916.37    85.7  899.53    95.2  895.74
   104.7  894.24   152.3  891.37   191.6  890.49   211.2  889.72   225.3  887.49
   230.8  886.45   240.7  886.03   250.5  887.35   260.3   888.9   270.1  889.63
   319.2  890.39   416.2  890.34   464.7  890.99   493.8  892.95   513.1  893.77
   522.8  896.24   561.4  915.47   590.3  931.19     600  936.17   609.6  940.95
   619.3  945.21   628.9  948.96   638.6  951.86   657.9  955.54   677.2     960
#Mann= 3 , 0 , 0
       0     .06       0   225.3    .045       0   250.5     .06       0
Bank Sta=225.3,250.5
XS Rating Curve= 0 ,0
Exp/Cntr=0.3,0.1

Chan Stop Cuts=-1
Use User Specified Reach Order=0
Composite Channel Slope=5